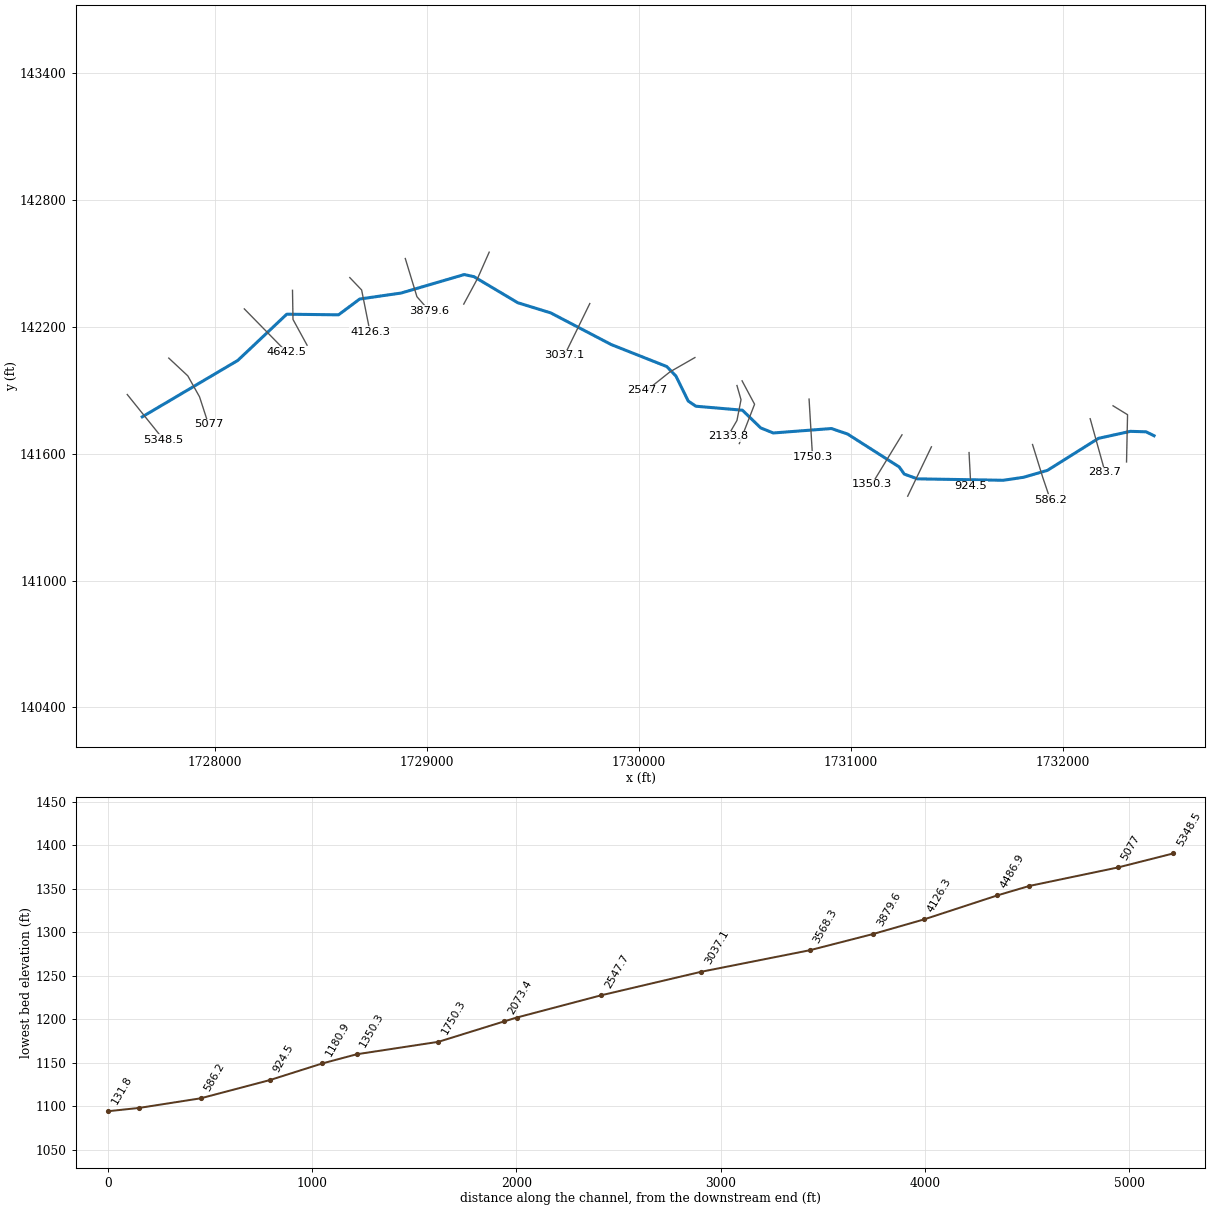
--- Beartown Branch.prj (project) ---

Proj Title=Beartown Branch
Current Plan=p01
Default Exp/Contr=0,0
English Units
Geom File=g01
Flow File=f01
Plan File=p01
BEGIN DESCRIPTION:
END DESCRIPTION:
DSS Export Rating Curves= 0
DSS Export Rating Curve Sorted= 0
DSS Export Volume Flow Curves= 0
DXF OffsetX= 0
DXF OffsetY= 0
DXF ScaleX= 0
DXF ScaleY= 0

--- Beartown Branch.p01 (plan) ---

Plan Title=Floodplain
Program Version=4.00
Geom File=g01
Flow File=f01
K Sum by GR=0
Std Step Tol=0.01
Critical Tol=0.01
Num of Std Step Trials=20
Max Error Tol=0.3
Flow Tol Ratio=0.001
Split Flow NTrial=30
Split Flow Tol=0.02
Split Flow Ratio=0.02
Log Output Level=0
Friction Slope Method=1
Unsteady Friction Slope Method=2
Unsteady Bridges Friction Slope Method=1
Global Log Level=0
CheckData=False
Run HTab=0
Run UNet=0
Run PostProcess=0
UNET Theta=0
UNET Theta Warmup=0
UNET ZTol=0
UNET ZSATol=0
UNET MxIter=0
UNET MaxInSteps=0
UNET DtIC=0
UNET DtMin=0
UNET MaxCRTS=0
UNET WFStab=0
UNET SFStab=0
UNET WFX=0
UNET SFX=0
UNET DSS MLevel=0
UNET DZMax Abort=0
UNET Convert EG Bridges=0
UNET Use Existing IB Tables=0
UNET Froude Limit=0
UNET Froude Power=0
Write IC File=0
Echo Input=False
Echo Output=False
Write Detailed=0

--- Beartown Branch.f01 (steady flow) ---

Flow Title=NFF Regression Equation
Program Version=4.00
Number of Profiles=1
Profile Names=P100yr
River Rch & RM=Beartown Branch,Main      ,5348.5
332.3958
River Rch & RM=Beartown Branch,Main      ,5077
694.1043
River Rch & RM=Beartown Branch,Main      ,4642.5
720.0952
River Rch & RM=Beartown Branch,Main      ,3568.3
800.0183
River Rch & RM=Beartown Branch,Main      ,2547.7
832.0405
River Rch & RM=Beartown Branch,Main      ,586.2
923.9316
River Rch & RM=Beartown Branch,Main      ,283.7
1038.371
Boundary for River Rch & Prof#=Beartown Branch,Main      ,1
Up Type=0
Dn Type=3
Dn Slope=0.041581

--- Beartown Branch.g01 (geometry) ---

Geom Title=Geometry
Program Version=4.00

River Reach=Beartown Branch ,Main
Reach XY= 30
     1727655.255      141773.638     1728106.408      142040.449
     1728337.321      142258.749     1728581.817      142255.839
      1728681.75      142330.546     1728876.765      142358.682
     1729175.211       142446.12     1729221.037      142436.181
     1729427.533      142313.057     1729583.234      142265.021
     1729869.302      142115.156     1730131.262      142011.343
      1730174.34      141966.518     1730232.478      141848.366
     1730268.425      141823.871     1730488.173      141805.098
     1730574.857      141721.175     1730633.935      141697.433
     1730908.343      141718.414     1730984.537      141692.464
     1731228.577      141536.764     1731252.319      141503.084
     1731313.963      141480.631     1731719.516      141473.839
     1731815.399      141488.028     1731928.125      141520.752
     1732168.853      141672.035     1732319.584      141705.163
     1732393.569      141702.954     1732431.419      141684.326

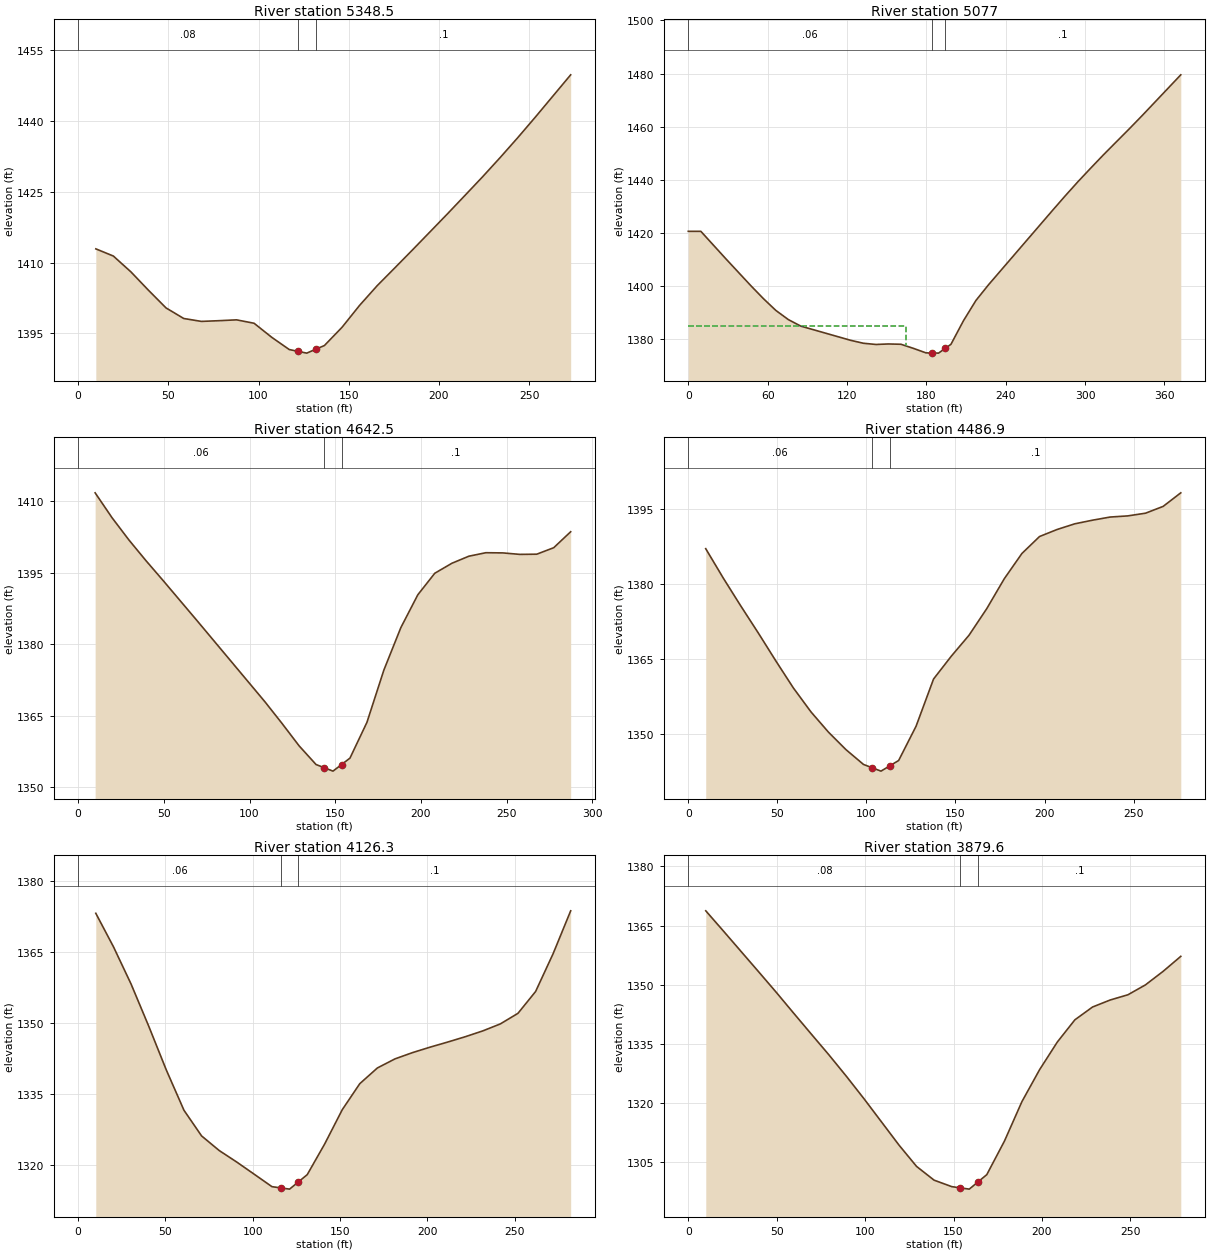
Type RM Length L Ch R = 1 ,5348.5  ,275,271.5,268
XS GIS Cut Line= 3
     1727584.503      141879.192     1727669.986      141772.774
      1727755.47      141666.355
#Sta/Elev= 30
     9.8 1412.92    19.5  1411.4    29.2 1408.06      39 1404.14    48.7 1400.41
    58.5 1398.17    68.3 1397.55      78  1397.7    87.8 1397.88    97.5 1397.16
   107.3 1394.18     117 1391.59   121.8 1391.21   126.7 1390.83   131.8 1391.67
   136.5 1392.44   146.3 1396.32     156 1400.95   165.8 1405.14   175.5 1408.88
   185.3 1412.69     195 1416.51   204.8 1420.38   214.5 1424.28   224.3 1428.24
     234  1432.3   243.7 1436.49   253.5 1440.87   263.2 1445.31     273 1449.79
#Mann= 3 , 0 , 0
       0     .08       0   121.8    .045       0   131.8      .1       0
Bank Sta=121.8,131.8
XS Rating Curve= 0 ,0
Exp/Cntr=0.3,0.1

Type RM Length L Ch R = 1 ,5077    ,429.3,434.6,439.9
XS GIS Cut Line= 4
     1727780.446      142051.377     1727870.253      141967.409
     1727925.687      141868.343     1727967.621      141739.047
#Sta/Elev= 30
       0 1420.57     9.5 1420.57    28.4 1410.23    47.3  1400.1    56.7 1395.27
    66.2 1390.78    75.7 1387.31    85.1 1384.86   122.9  1379.5   132.4 1378.41
   141.9 1377.95   151.3 1378.14   160.8 1378.03   170.2 1376.49   179.7 1374.79
   184.2 1374.74   189.2 1374.69   194.2 1376.45   198.6    1378   208.1 1386.91
   217.5 1394.52     227 1400.42   275.3 1428.38     285 1433.91   294.7 1439.29
   304.4 1444.42   314.1 1449.47   333.6 1459.24   343.3 1464.21   372.4 1479.51
#Mann= 3 , 0 , 0
       0     .06       0   184.2    .045       0   194.2      .1       0
#XS Ineff= 2 , 0
          164.73 1384.72
Permanent Ineff=
       F       F
Bank Sta=184.2,194.2
XS Rating Curve= 0 ,0
Exp/Cntr=0.3,0.1

Type RM Length L Ch R = 1 ,4642.5  ,170.9,155.5,140.1
XS GIS Cut Line= 2
     1728136.964      142283.936     1728338.052      142078.546
#Sta/Elev= 27
     9.9 1411.77    19.8 1406.53    29.7 1401.84    39.6 1397.52    49.6 1393.35
    69.4 1384.93     109 1367.91   118.9  1363.4   128.9 1358.68   138.8 1354.75
   143.7 1354.06   148.7 1353.36   153.7 1354.74   158.6 1356.09   168.5 1363.59
   178.4 1374.58   188.3 1383.48   198.2 1390.37   208.1 1394.89   218.1 1396.99
     228 1398.47   237.9  1399.2   247.8 1399.16   257.7 1398.85   267.6 1398.89
   277.5 1400.25   287.4  1403.6
#Mann= 3 , 0 , 0
       0     .06       0   143.7    .045       0   153.7      .1       0
Bank Sta=143.7,153.7
XS Rating Curve= 0 ,0
Exp/Cntr=0.3,0.1

Type RM Length L Ch R = 1 ,4486.9  ,356.9,360.6,364.3
XS GIS Cut Line= 3
     1728364.494      142371.748     1728366.847       142234.02
     1728433.287      142112.246
#Sta/Elev= 30
     9.8 1387.02    19.7 1381.12    29.5 1375.57    39.4 1370.13    49.2 1364.58
      59  1359.2    68.9 1354.41    78.7 1350.37    88.6 1346.85    98.4 1343.91
   103.2 1343.26   108.2 1342.58   113.2 1343.65   118.1  1344.7   127.9 1351.56
   137.7 1360.98   147.7 1365.56   157.6 1369.72   167.5    1375   177.4 1381.01
   187.3 1386.06   197.2 1389.45   207.1 1390.86     217 1391.99   226.9 1392.71
   236.8 1393.34   246.7 1393.57   256.7 1394.11   266.6 1395.47   276.5 1398.18
#Mann= 3 , 0 , 0
       0     .06       0   103.2    .045       0   113.2      .1       0
Bank Sta=103.2,113.2
XS Rating Curve= 0 ,0
Exp/Cntr=0.3,0.1

Type RM Length L Ch R = 1 ,4126.3  ,244.8,246.7,248.7
XS GIS Cut Line= 3
     1728634.988      142431.751     1728690.807      142373.265
     1728730.295      142175.928
#Sta/Elev= 30
    10.1 1373.19    20.2 1366.12    30.3 1358.23    40.4 1349.33    50.5 1340.04
    60.6 1331.53    70.7  1326.1    80.8 1323.01    90.9 1320.56     101 1317.96
     111 1315.37   116.1 1315.11   121.1 1314.85   126.1 1316.37   131.2 1317.91
   141.2  1324.4   151.3 1331.67   161.3 1337.15   171.4 1340.48   181.5  1342.4
   191.5 1343.72   201.6 1344.88   211.7 1345.96   221.7 1347.08   231.8 1348.32
   241.8 1349.79   251.9 1352.03     262 1356.64     272 1364.61   282.1 1373.71
#Mann= 3 , 0 , 0
       0     .06       0   116.1    .045       0   126.1      .1       0
Bank Sta=116.1,126.1
XS Rating Curve= 0 ,0
Exp/Cntr=0.3,0.1

Type RM Length L Ch R = 1 ,3879.6  ,325.6,311.2,295.3
XS GIS Cut Line= 3
     1728896.918      142521.916     1728951.857      142341.393
     1729011.144      142273.961
#Sta/Elev= 30
     9.9 1368.72    19.9 1363.59    29.8 1358.46    39.7 1353.33    49.7 1348.11
    59.6  1342.8    69.5 1337.54    79.5 1332.26    89.4 1326.82    99.3 1321.17
   109.2  1315.3   119.2 1309.37   129.1 1303.99     139 1300.51     149 1298.87
   153.9 1298.55   158.9 1298.24   163.9 1300.09   168.8 1301.91   178.8 1310.42
   188.7 1320.43   198.7 1328.52   208.7  1335.5   218.6 1341.11   228.6 1344.36
   238.6 1346.14   248.6 1347.46   258.5 1349.96   268.5 1353.39   278.5 1357.19
#Mann= 3 , 0 , 0
       0     .08       0   153.9    .045       0   163.9      .1       0
Bank Sta=153.9,163.9
XS Rating Curve= 0 ,0
Exp/Cntr=0.3,0.1

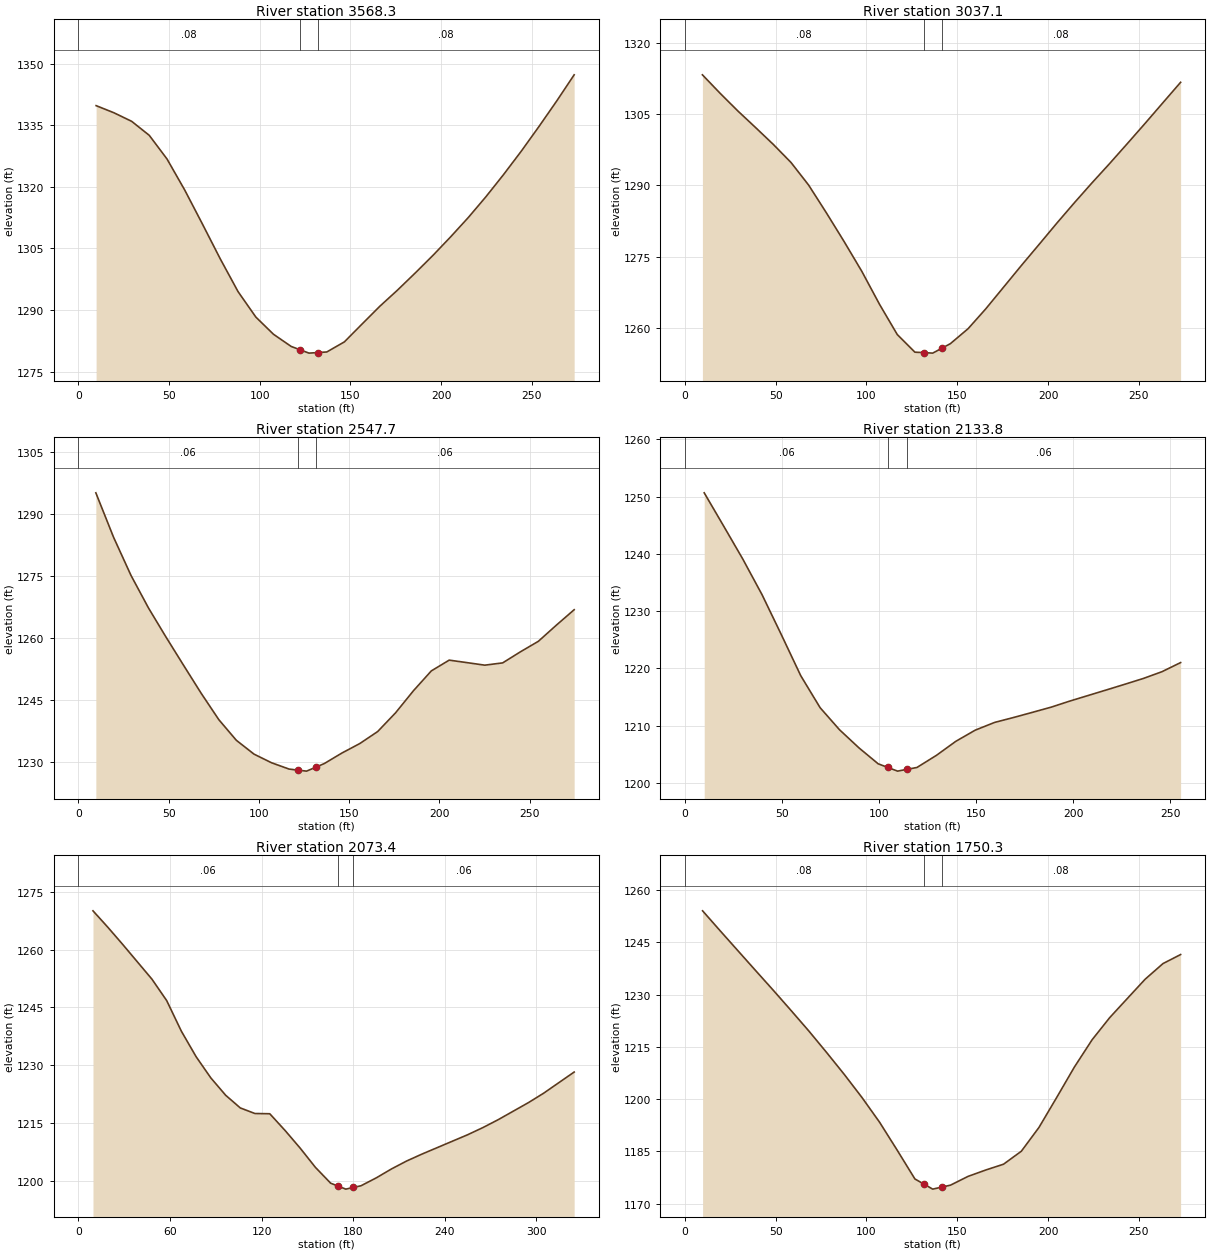
Type RM Length L Ch R = 1 ,3568.3  ,532,531.2,532
XS GIS Cut Line= 3
     1729292.924      142551.971     1729237.562      142426.649
      1729172.89      142306.544
#Sta/Elev= 30
     9.8  1339.8    19.6 1338.07    29.4 1335.98    39.1 1332.57    48.9  1326.8
    58.7 1319.21    68.5 1310.89    78.3 1302.43    88.1 1294.46    97.9 1288.27
   107.6 1284.09   117.4 1281.11   122.2 1280.32   127.2 1279.49   132.2 1279.63
     137 1279.77   146.7 1282.23   156.5  1286.6   166.2 1290.89     176 1294.85
   185.7 1298.99   195.5 1303.29   205.2 1307.78     215 1312.52   224.7 1317.57
   234.4 1322.96   244.2 1328.68   253.9 1334.65   263.7 1340.88   273.4 1347.31
#Mann= 3 , 0 , 0
       0     .08       0   122.2    .045       0   132.2     .08       0
Bank Sta=122.2,132.2
XS Rating Curve= 0 ,0
Exp/Cntr=0.3,0.1

Type RM Length L Ch R = 1 ,3037.1  ,501.4,489.4,479.1
XS GIS Cut Line= 3
     1729767.886      142309.171     1729707.946      142186.536
     1729648.006        142063.9
#Sta/Elev= 30
     9.7 1313.24    19.5 1309.34    29.2 1305.65      39 1302.15    48.8 1298.59
    58.5 1294.81    68.2 1290.06      78 1284.21    87.7 1278.21    97.5 1271.92
   107.2 1265.02     117 1258.65   126.7 1254.95   131.5 1254.86   136.5 1254.75
   141.5 1255.77   146.2 1256.73     156 1259.89   165.7 1264.05   175.5  1268.6
   185.2 1273.11     195 1277.56   204.7    1282   214.5 1286.35   224.2 1290.53
     234 1294.63   243.7  1298.8   253.5 1303.06   263.2 1307.35     273 1311.67
#Mann= 3 , 0 , 0
       0     .08       0   131.5    .045       0   141.5     .08       0
Bank Sta=131.5,141.5
XS Rating Curve= 0 ,0
Exp/Cntr=0.3,0.1

Type RM Length L Ch R = 1 ,2547.7  ,396.6,414,429.6
XS GIS Cut Line= 3
     1730264.084      142053.917     1730146.018      141986.092
     1730037.789      141899.789
#Sta/Elev= 30
     9.7 1295.19    19.5 1284.43    29.2 1275.14    38.9 1267.24    48.6 1260.19
    58.4  1253.3    68.1 1246.55    77.8  1240.2    87.5  1235.2    97.3 1231.84
     107 1229.75   116.7 1228.22   121.4 1227.97   126.4 1227.72   131.4 1228.65
   136.2 1229.55     146 1232.11   155.9 1234.41   165.8 1237.32   175.7 1241.86
   185.6 1247.21   195.5 1252.02   205.4 1254.63   215.3 1254.02   225.1 1253.41
     235 1253.96   244.9 1256.66   254.8  1259.2   264.7 1263.09   274.6 1266.85
#Mann= 3 , 0 , 0
       0     .06       0   121.4    .045       0   131.4     .06       0
Bank Sta=121.4,131.4
XS Rating Curve= 0 ,0
Exp/Cntr=0.3,0.1

Type RM Length L Ch R = 1 ,2133.8  ,63.5,60.4,57.2
XS GIS Cut Line= 4
     1730462.485      141921.647     1730481.624      141854.661
     1730462.485      141756.573     1730419.423      141682.409
#Sta/Elev= 28
      10 1250.65    19.9 1244.92    29.9 1239.08    39.8 1232.87    49.8 1225.85
    59.7 1218.76    69.7 1213.16    79.7 1209.31    89.7 1206.15    99.6 1203.37
   104.6 1202.73   109.6 1202.09   114.6 1202.41   119.6 1202.73   129.6 1204.84
   139.6 1207.29   149.6 1209.24   159.6 1210.59   169.6 1211.47   179.1 1212.35
   188.7 1213.25   198.2  1214.3   207.7 1215.28   217.2 1216.26   226.8 1217.26
   236.3 1218.27   245.8 1219.44   255.4 1221.03
#Mann= 3 , 0 , 0
       0     .06       0   104.6    .045       0   114.6     .06       0
Bank Sta=104.6,114.6
XS Rating Curve= 0 ,0
Exp/Cntr=0.3,0.1

Type RM Length L Ch R = 1 ,2073.4  ,314.4,323.1,331.7
XS GIS Cut Line= 3
     1730486.682      141943.797     1730545.667      141833.142
     1730473.574       141647.22
#Sta/Elev= 30
     9.6 1270.06    19.3 1265.81    28.9 1261.41    48.2 1252.32    57.9 1246.73
    67.5 1238.79    77.2 1232.14    86.8 1226.66    96.5 1222.16   106.1 1218.86
   115.7 1217.41   125.4 1217.35   135.4 1213.02   145.3 1208.43   155.3 1203.43
   165.3 1199.31   170.2 1198.55   175.2 1197.77   180.2 1198.21   185.2 1198.65
   195.2  1200.7   205.2 1203.03   215.1 1205.08   225.1 1206.87     255 1211.89
     265 1213.75     275  1215.8   294.9 1220.25   304.9 1222.71   324.8 1228.18
#Mann= 3 , 0 , 0
       0     .06       0   170.2    .045       0   180.2     .06       0
Bank Sta=170.2,180.2
XS Rating Curve= 0 ,0
Exp/Cntr=0.3,0.1

Type RM Length L Ch R = 1 ,1750.3  ,412.2,400,387.8
XS GIS Cut Line= 3
     1730802.881      141857.621     1730811.056      141721.366
     1730819.231      141585.111
#Sta/Elev= 30
     9.8 1254.01    19.5 1248.27    29.3 1242.54      39 1236.87    48.8 1231.18
    58.5 1225.43    68.3 1219.54      78 1213.43    87.8 1207.09    97.5  1200.5
   107.2 1193.41     117 1185.31   126.7  1177.1   131.5 1175.67   136.5 1174.18
   141.5 1174.76   146.3 1175.32     156 1177.84   165.8 1179.68   175.5 1181.33
   185.3 1185.05     195 1191.87   204.8  1200.5   214.5 1209.19   224.3 1217.05
     234  1223.4   243.8 1228.94   253.5 1234.41   263.3 1238.88     273 1241.47
#Mann= 3 , 0 , 0
       0     .08       0   131.5    .045       0   141.5     .08       0
Bank Sta=131.5,141.5
XS Rating Curve= 0 ,0
Exp/Cntr=0.3,0.1

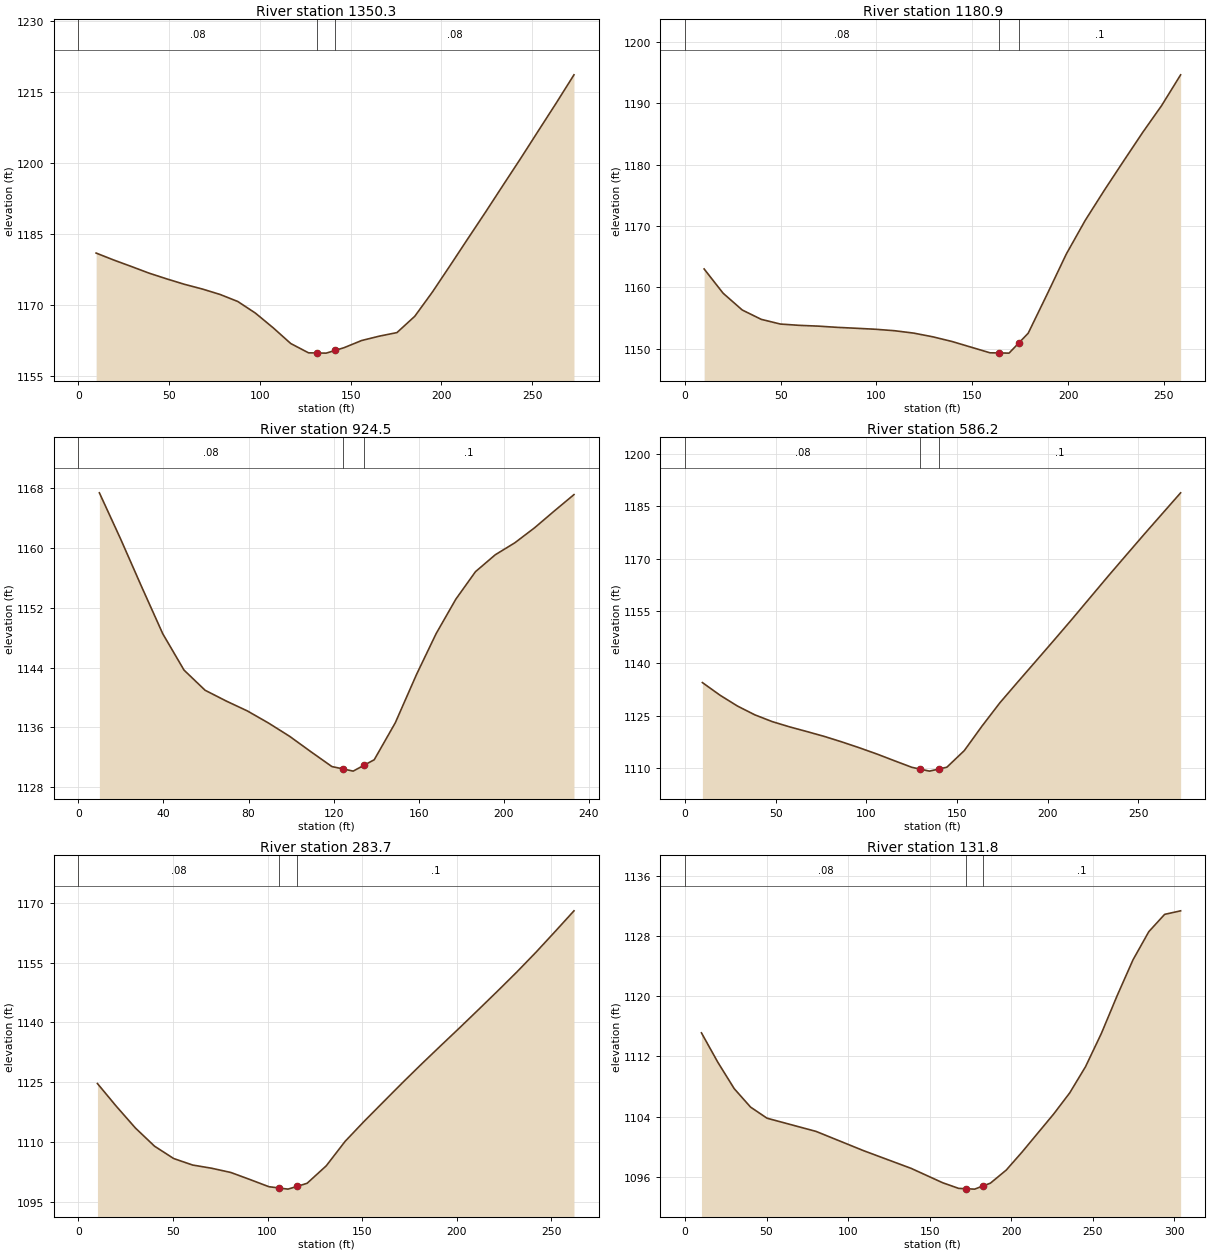
Type RM Length L Ch R = 1 ,1350.3  ,167.4,169.4,171.4
XS GIS Cut Line= 3
     1731241.522      141688.683     1731170.549      141572.085
     1731099.577      141455.487
#Sta/Elev= 30
     9.8 1181.02    19.5 1179.55    29.3 1178.17      39 1176.77    48.8 1175.55
    58.5 1174.41    68.3 1173.42      78 1172.28    87.8 1170.79    97.5 1168.34
   107.3 1165.23     117  1161.9   126.8 1159.93   131.5  1159.9   136.5 1159.87
   141.5 1160.45   146.3 1161.01     156 1162.53   165.8 1163.46   175.5 1164.21
   185.3 1167.65     195 1172.77   204.8 1178.39   214.5 1184.03   224.3 1189.68
     234 1195.39   243.8 1201.12   253.5 1206.93   263.3 1212.77     273 1218.69
#Mann= 3 , 0 , 0
       0     .08       0   131.5    .045       0   141.5     .08       0
Bank Sta=131.5,141.5
XS Rating Curve= 0 ,0
Exp/Cntr=0.3,0.1

Type RM Length L Ch R = 1 ,1180.9  ,246.3,256.5,266.5
XS GIS Cut Line= 2
      1731380.42      141632.042     1731268.487      141398.691
#Sta/Elev= 28
      10 1162.98    19.9 1159.03    29.9 1156.29    39.8 1154.77    49.8    1154
    59.7 1153.79    69.7 1153.66    79.6 1153.46    89.6 1153.31    99.5 1153.15
   109.5 1152.91   119.5 1152.52   129.4 1151.92   139.4 1151.16   149.3 1150.24
   159.3 1149.31   164.2 1149.29   169.2 1149.26   174.2 1150.88   179.2  1152.5
   189.1 1158.86   199.1 1165.41     209 1170.91     219 1175.83   228.9 1180.52
   238.9  1185.2   248.9 1189.63   258.8 1194.63
#Mann= 3 , 0 , 0
       0     .08       0   164.2    .045       0   174.2      .1       0
Bank Sta=164.2,174.2
XS Rating Curve= 0 ,0
Exp/Cntr=0.3,0.1

Type RM Length L Ch R = 1 ,924.5   ,333.2,338.2,343.2
XS GIS Cut Line= 2
     1731558.008      141604.873     1731566.342       141446.12
#Sta/Elev= 26
     9.9 1167.35    19.9 1161.17    29.8 1154.77    39.7 1148.51    49.7 1143.65
    59.6 1140.96    69.6 1139.51    79.5 1138.19    89.4 1136.58    99.4 1134.79
   109.3 1132.75   119.2 1130.76   124.2 1130.46   129.2 1130.15   134.2 1130.92
   139.1 1131.67     149 1136.61     159 1143.08   168.2 1148.53   177.5 1153.15
   186.7 1156.81     196 1159.07   205.2 1160.67   214.5 1162.68   223.7 1164.91
     233 1167.11
#Mann= 3 , 0 , 0
       0     .08       0   124.2    .045       0   134.2      .1       0
Bank Sta=124.2,134.2
XS Rating Curve= 0 ,0
Exp/Cntr=0.3,0.1

Type RM Length L Ch R = 1 ,586.2   ,303.2,302.6,301.9
XS GIS Cut Line= 3
     1731857.723      141642.876     1731906.237      141486.579
     1731941.504      141382.809
#Sta/Elev= 30
     9.6 1134.53    19.3 1130.93    28.9 1127.83    38.5 1125.31    48.1 1123.37
    57.8 1121.85    67.4  1120.5      77 1119.11    86.6 1117.55    96.3 1115.86
   105.9 1114.09   115.5 1112.18   125.1  1110.3   129.8 1109.77   134.8 1109.21
   139.8 1109.79   144.4 1110.33     154 1115.07   163.7 1122.03   173.6 1128.73
   183.6 1134.76   193.5 1140.67   203.5 1146.66   213.5 1152.71   223.4 1158.83
   233.4    1165   243.4 1171.04   253.3 1176.99   263.3  1182.9   273.3 1188.79
#Mann= 3 , 0 , 0
       0     .08       0   129.8    .045       0   139.8      .1       0
Bank Sta=129.8,139.8
XS Rating Curve= 0 ,0
Exp/Cntr=0.3,0.1

Type RM Length L Ch R = 1 ,283.7   ,157.8,151.9,146
XS GIS Cut Line= 2
     1732129.801      141764.844     1732199.996      141512.521
#Sta/Elev= 28
    10.1 1124.62    20.1  1118.9    30.2 1113.44    40.3 1108.88    50.4 1105.79
    60.4 1104.16    70.5 1103.35    80.6 1102.29    90.7 1100.52   100.7 1098.72
   105.8 1098.41   110.8 1098.11   115.8 1098.83   120.9 1099.58     131 1103.96
     141 1110.12   151.1 1115.17   161.2 1120.01   171.2 1124.79   181.3 1129.49
   191.4 1134.08   201.5 1138.63   211.5 1143.21   221.6 1147.87   231.7 1152.62
   241.8 1157.58   251.8 1162.72   261.9 1167.99
#Mann= 3 , 0 , 0
       0     .08       0   105.8    .045       0   115.8      .1       0
Bank Sta=105.8,115.8
XS Rating Curve= 0 ,0
Exp/Cntr=0.3,0.1

Type RM Length L Ch R = 1 ,131.8   ,140.5,131.8,123
XS GIS Cut Line= 3
     1732237.708      141825.889     1732306.238      141783.816
      1732301.42      141560.427
#Sta/Elev= 25
    10.1 1115.14    20.1 1111.24    30.2 1107.71    40.2 1105.26    50.3 1103.78
    80.4 1102.02   109.6 1099.45   138.7  1097.1   158.1 1095.18   167.8 1094.44
   172.6 1094.39   177.6 1094.34   182.6 1094.75   187.3 1095.14     197 1096.88
   206.7 1099.28   226.1 1104.35   235.9 1107.15   245.6 1110.64   255.3 1115.06
     265  1120.1   274.7 1124.86   284.4 1128.61   294.1 1130.91   303.9 1131.38
#Mann= 3 , 0 , 0
       0     .08       0   172.6    .045       0   182.6      .1       0
Bank Sta=172.6,182.6
XS Rating Curve= 0 ,0
Exp/Cntr=0.3,0.1

Chan Stop Cuts=-1
Use User Specified Reach Order=0